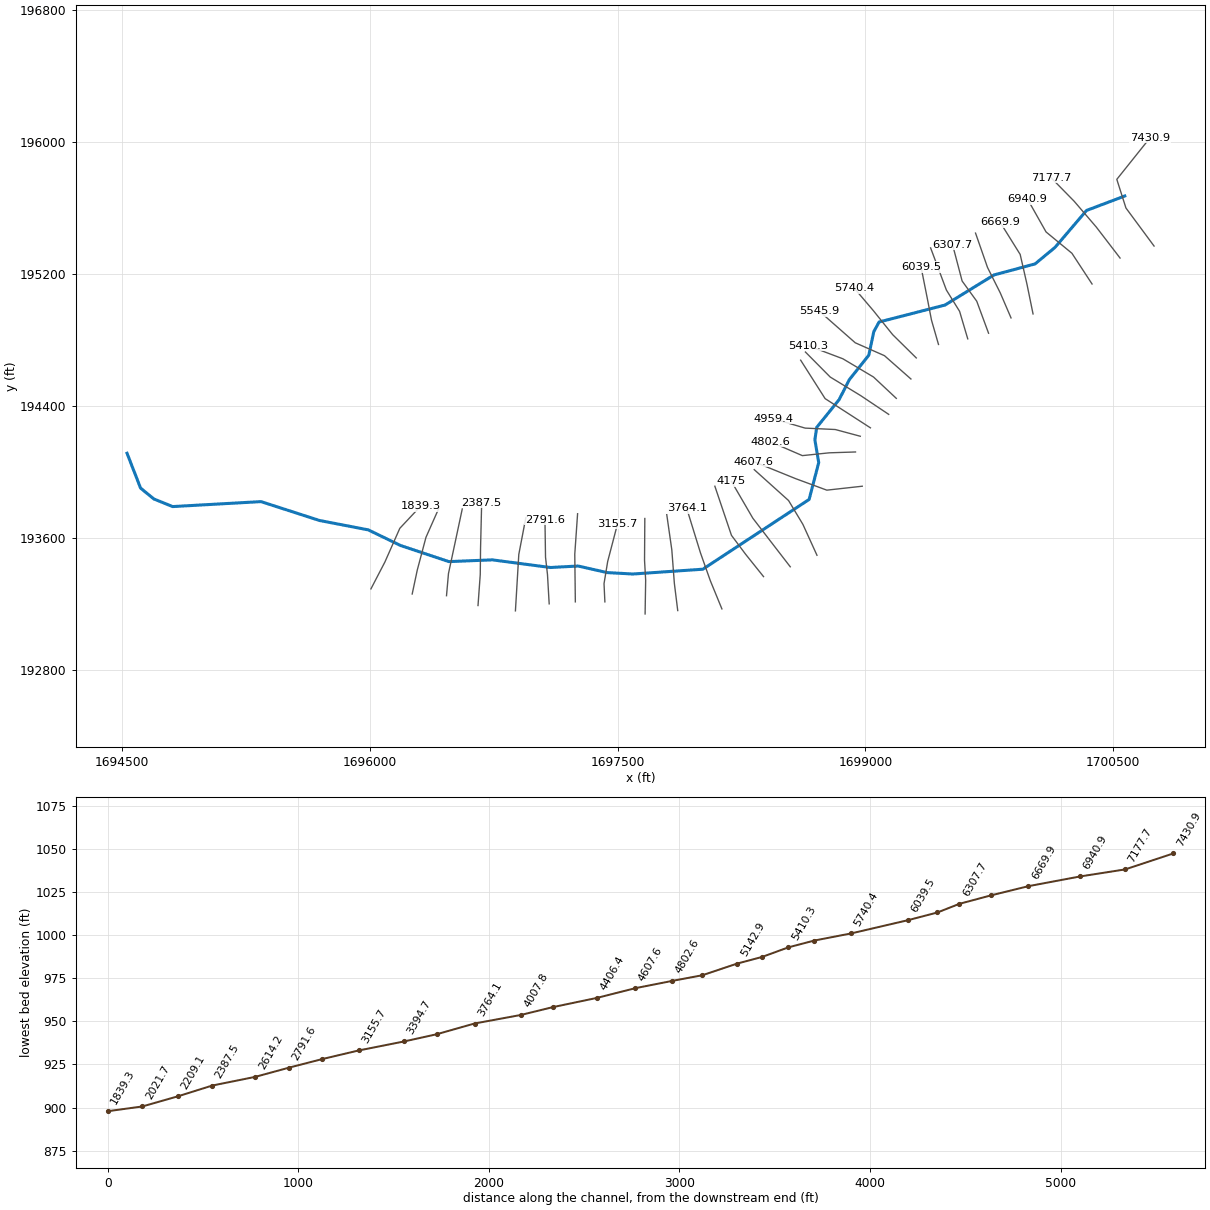
--- trkycrk1.prj (project) ---

Proj Title=trkycrk1
Current Plan=p01
Default Exp/Contr=0,0
English Units
Geom File=g01
Flow File=f01
Plan File=p01
BEGIN DESCRIPTION:
END DESCRIPTION:
DSS Export Rating Curves= 0
DSS Export Rating Curve Sorted= 0
DSS Export Volume Flow Curves= 0
DXF OffsetX= 0
DXF OffsetY= 0
DXF ScaleX= 0
DXF ScaleY= 0

--- trkycrk1.p01 (plan) ---

Plan Title=Floodplain
Program Version=4.00
Geom File=g01
Flow File=f01
K Sum by GR=0
Std Step Tol=0.01
Critical Tol=0.01
Num of Std Step Trials=20
Max Error Tol=0.3
Flow Tol Ratio=0.001
Split Flow NTrial=30
Split Flow Tol=0.02
Split Flow Ratio=0.02
Log Output Level=0
Friction Slope Method=1
Unsteady Friction Slope Method=2
Unsteady Bridges Friction Slope Method=1
Global Log Level=0
CheckData=False
Run HTab=0
Run UNet=0
Run PostProcess=0
UNET Theta=0
UNET Theta Warmup=0
UNET ZTol=0
UNET ZSATol=0
UNET MxIter=0
UNET MaxInSteps=0
UNET DtIC=0
UNET DtMin=0
UNET MaxCRTS=0
UNET WFStab=0
UNET SFStab=0
UNET WFX=0
UNET SFX=0
UNET DSS MLevel=0
UNET DZMax Abort=0
UNET Convert EG Bridges=0
UNET Use Existing IB Tables=0
UNET Froude Limit=0
UNET Froude Power=0
Write IC File=0
Echo Input=False
Echo Output=False
Write Detailed=0

--- trkycrk1.f01 (steady flow) ---

Flow Title=NFF Regression Equation
Program Version=4.00
Number of Profiles= 1
Profile Names=P100yr
River Rch & RM=trkycrk1,Main            ,7430.9
     309
River Rch & RM=trkycrk1,Main            ,7177.7
     477
River Rch & RM=trkycrk1,Main            ,6472.3
     486
River Rch & RM=trkycrk1,Main            ,4406.4
     538
River Rch & RM=trkycrk1,Main            ,4175
     609
River Rch & RM=trkycrk1,Main            ,3155.7
     626
Boundary for River Rch & Prof#=trkycrk1,Main            , 1
Up Type= 0
Dn Type= 3
Dn Slope=0.01
DSS Import GetInterval= 0
DSS Import GetPeak= 0
DSS Import FillOption= 0

--- trkycrk1.g01 (geometry) ---

Geom Title=USGS 10m DEM
Program Version=4.00

River Reach=trkycrk1        ,Main
Reach XY= 30
     1700570.255       195674.55     1700338.563      195586.759
     1700147.606      195362.494     1700027.066      195262.608
     1699778.414      195195.502     1699481.985      195013.074
     1699082.848      194910.183     1699050.705      194851.108
     1699020.793      194709.113     1698902.819       194560.37
      1698841.13      194439.632     1698705.155      194270.498
     1698694.239      194195.217     1698717.554      194057.632
     1698659.399      193833.876     1698015.975      193410.649
     1697592.854      193381.519     1697436.393      193390.239
     1697261.041      193429.978     1697093.512      193420.986
       1696741.6      193467.396     1696478.909      193456.745
     1696185.475      193554.825     1695990.845       193649.28
     1695695.539       193706.24     1695341.602      193820.693
     1694806.752      193790.544     1694693.311      193836.629
     1694612.695      193902.525      1694530.55      194114.028

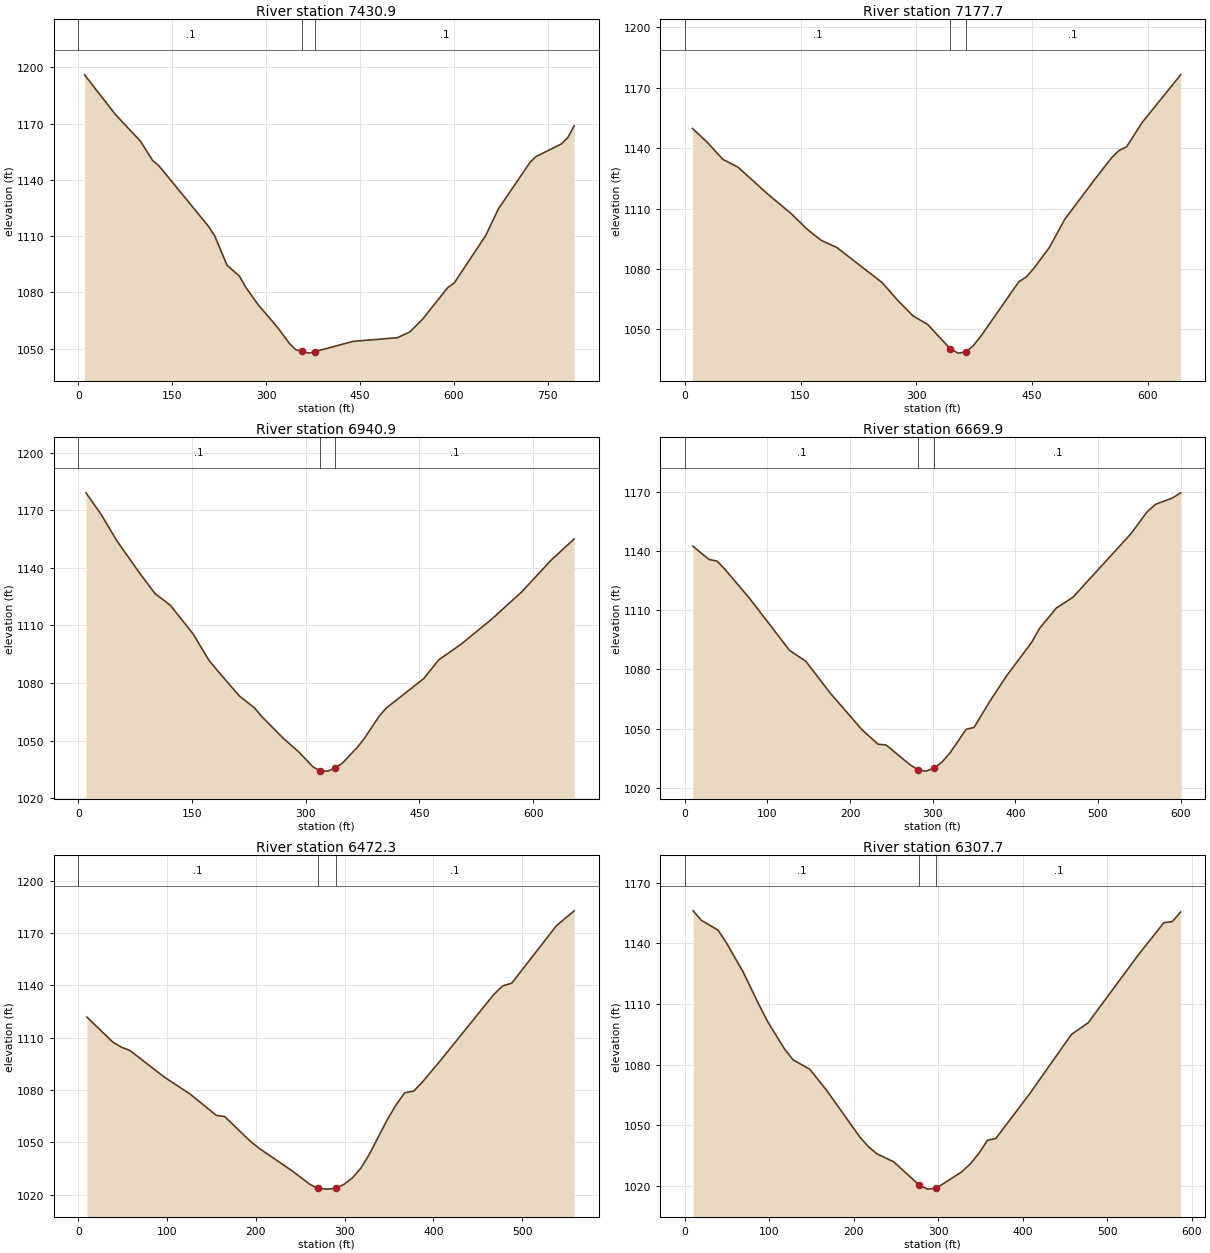
Type RM Length L Ch R = 1 ,7430.9  ,243.2,253.3,263.3
XS GIS Cut Line= 4
     1700747.374       195370.83     1700577.096      195601.762
     1700521.888      195775.459     1700723.158      196027.705
#Sta/Elev= 30
     9.9 1195.98    59.4 1174.75    98.9 1160.71   118.7  1150.3   128.6  1147.5
   207.8 1115.22   217.7 1110.19   237.5 1094.42   257.2 1088.67   267.1 1082.84
   286.9 1073.47   317.3 1061.63   337.6 1052.55   347.7 1049.26   357.9 1048.45
   367.9 1047.54   377.9 1048.34   438.8 1053.82   509.5 1055.76   529.7 1058.89
   549.9  1065.7   590.2 1082.54   600.3 1084.91   650.7  1110.3   670.9 1124.46
   721.3 1149.25   731.4 1152.46   771.7 1159.16   781.8 1162.54   791.9 1168.78
#Mann= 3 , 0 , 0
       0      .1       0   357.9    .045       0   377.9      .1       0
Bank Sta=357.9,377.9
XS Rating Curve= 0 ,0
Exp/Cntr=0.3,0.1

Type RM Length L Ch R = 1 ,7177.7  ,232.5,236.8,241.1
XS GIS Cut Line= 4
     1700541.534       195298.18     1700397.742      195485.977
     1700263.794      195642.628     1700123.798      195785.539
#Sta/Elev= 30
     9.9 1149.77    29.6  1142.7    49.3 1134.44      69 1130.53   108.4 1116.88
     138 1107.46   157.7 1100.09   167.5 1096.98   177.4 1094.11   197.1 1090.66
   256.2 1073.12   275.8 1064.52   295.4 1056.88     315 1052.41   344.3 1040.32
   354.3 1038.25   364.3  1038.8   373.9 1041.94   383.7  1046.6   432.8  1073.6
   442.6 1076.06   452.6 1080.38   472.6  1090.7   492.6 1104.75   532.7 1125.12
   552.7 1134.94   562.7 1138.81   572.7 1140.65   592.7 1152.65   642.7 1176.37
#Mann= 3 , 0 , 0
       0      .1       0   344.3    .045       0   364.3      .1       0
Bank Sta=344.3,364.3
XS Rating Curve= 0 ,0
Exp/Cntr=0.3,0.1

Type RM Length L Ch R = 1 ,6940.9  ,287.4,271,254.5
XS GIS Cut Line= 4
     1700372.017      195140.772     1700250.172      195327.056
     1700093.521      195456.463     1699981.525      195655.375
#Sta/Elev= 30
    10.1 1179.03    30.4  1167.6    50.6  1154.2    80.9 1137.22   101.2 1126.62
   121.4 1120.48   151.8 1105.34     172 1092.04   182.1 1087.14   212.5 1073.25
   232.3  1067.1   241.9  1062.6     271 1051.01   290.3 1044.34   309.7 1036.33
     319 1034.31     329 1034.15     339  1035.8   348.4 1038.35   367.7 1046.39
   377.4 1051.19   396.8 1062.73   406.4 1067.05   455.6  1082.3   475.4 1092.06
   505.2 1100.31   544.9 1113.13   584.6 1127.35   624.3 1144.21   654.1 1155.01
#Mann= 3 , 0 , 0
       0      .1       0     319    .045       0     339      .1       0
Bank Sta=319,339
XS Rating Curve= 0 ,0
Exp/Cntr=0.3,0.1

Type RM Length L Ch R = 1 ,6669.9  ,191.6,197.6,203.6
XS GIS Cut Line= 4
     1700014.823      194959.148     1699977.735       195140.89
      1699936.87      195320.245     1699815.036      195516.129
#Sta/Elev= 30
     9.8 1142.35    29.3 1135.67    39.1 1134.81    48.8 1130.57    78.1 1116.13
   126.9 1089.57   146.4 1084.17   175.7 1068.19   214.5 1049.45   233.9 1042.15
   243.6 1041.74   272.6 1031.76     282 1029.19     292 1028.51     302  1030.1
   311.3 1033.14     321 1037.74   340.4 1049.65   350.1 1050.64   369.4    1064
   389.5 1076.77   419.6 1093.58   429.6 1100.88   449.7 1111.06   469.7  1116.5
   539.9 1148.64     560    1160     570 1163.61   590.1 1166.77   600.1 1169.38
#Mann= 3 , 0 , 0
       0      .1       0     282    .045       0     302      .1       0
Bank Sta=282,302
XS Rating Curve= 0 ,0
Exp/Cntr=0.3,0.1

Type RM Length L Ch R = 1 ,6472.3  ,160.5,164.6,168.6
XS GIS Cut Line= 4
     1699881.632      194934.931     1699816.544      195086.403
     1699739.353      195240.784     1699666.709      195449.534
#Sta/Elev= 30
     9.7 1121.75    38.8 1107.46    48.5 1104.51    58.2 1102.62      97 1087.31
   126.1 1077.57   155.2 1065.49   164.9 1064.72   193.6 1050.65   203.2 1046.71
   241.6 1033.32   260.8 1025.87   269.9 1023.59   279.9 1023.13   289.9 1023.59
   299.1 1025.82   308.7 1029.57   318.3  1035.2   327.9  1043.2   347.5 1062.46
   357.6 1071.22   367.6 1078.35   377.7 1079.32   387.7 1084.63   407.8 1096.81
   468.1 1134.81   478.1 1139.68   488.2 1141.22   538.4 1174.07   558.5 1182.69
#Mann= 3 , 0 , 0
       0      .1       0   269.9    .045       0   289.9      .1       0
Bank Sta=269.9,289.9
XS Rating Curve= 0 ,0
Exp/Cntr=0.3,0.1

Type RM Length L Ch R = 1 ,6307.7  ,116.5,114.7,113
XS GIS Cut Line= 4
     1699745.597      194842.062     1699674.082      195036.173
      1699585.54      195158.769     1699527.464      195379.911
#Sta/Elev= 30
     9.9 1156.17    19.7 1151.41    39.4  1146.6    49.3  1140.3      69  1125.9
    88.7 1108.84    98.5 1100.95   118.2 1087.58   128.1 1082.32   147.8  1077.7
   167.5 1067.39   206.9  1044.2   216.9 1039.48     227 1035.85   247.2 1031.78
   277.5 1020.21   287.5 1018.25   297.5  1018.7   327.8 1026.84   337.9 1030.81
     348    1036   358.1 1042.44     368 1043.34   407.8 1065.36   457.5 1094.91
   477.4 1100.74     537 1134.55   566.9  1150.3   576.8 1150.81   586.7 1155.59
#Mann= 3 , 0 , 0
       0      .1       0   277.5    .045       0   297.5      .1       0
Bank Sta=277.5,297.5
XS Rating Curve= 0 ,0
Exp/Cntr=0.3,0.1

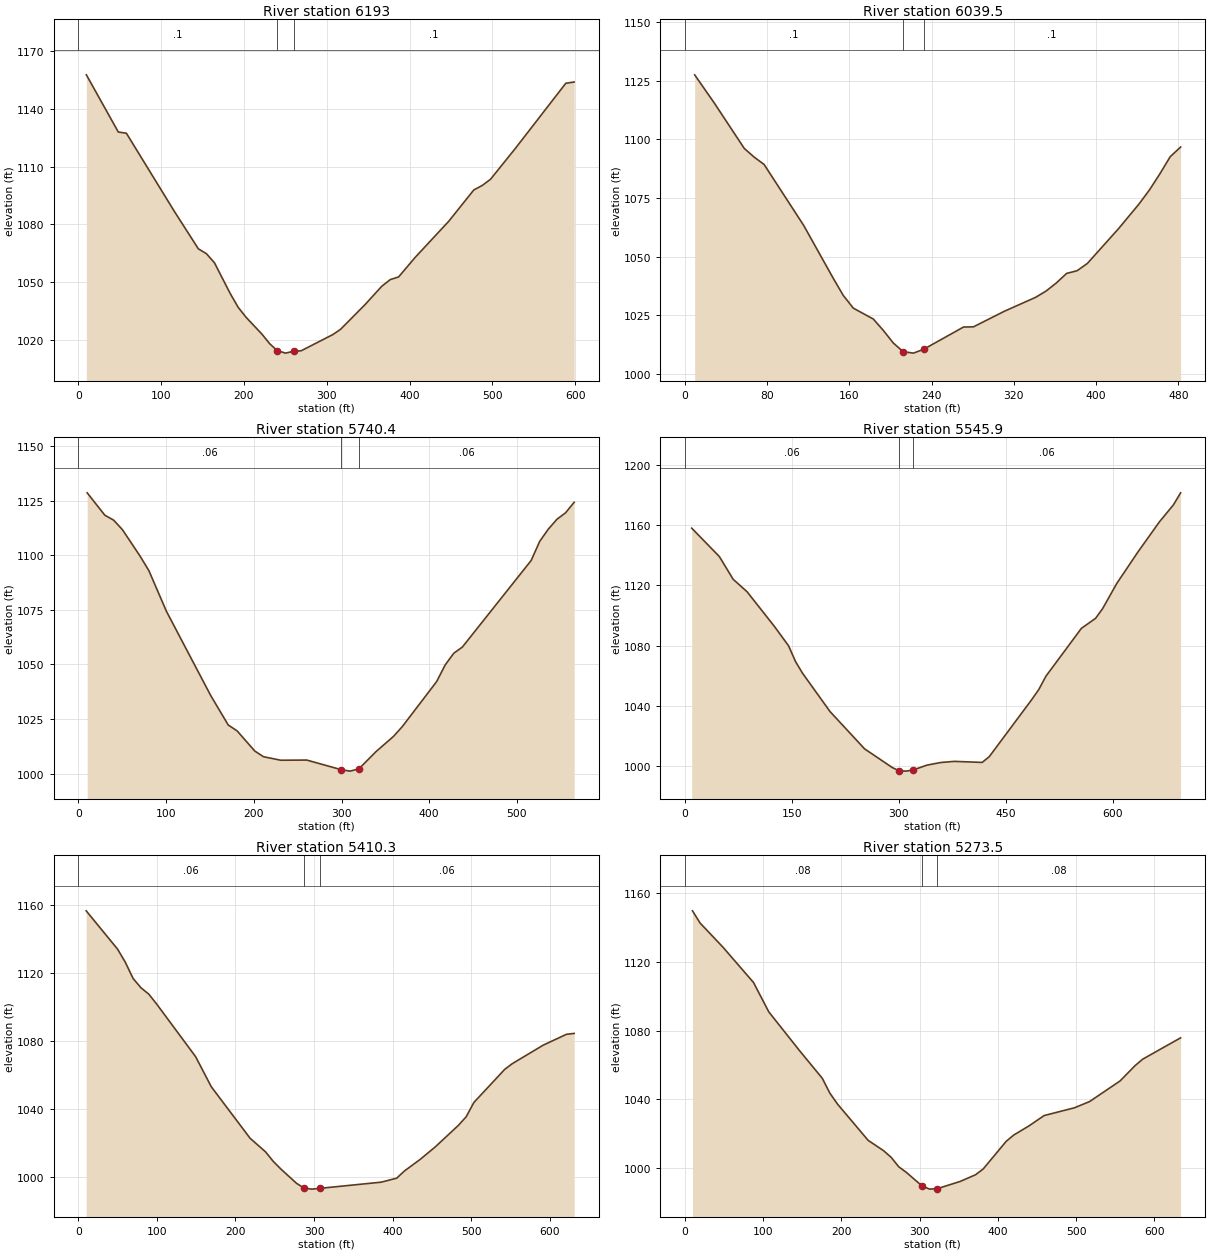
Type RM Length L Ch R = 1 ,6193    ,162.6,153.5,144.4
XS GIS Cut Line= 4
     1699619.595      194808.007     1699570.215      194974.874
     1699490.187      195104.282     1699394.835      195359.691
#Sta/Elev= 30
     9.7 1157.62    48.3 1127.93      58 1127.35     116 1086.76     145 1067.34
   154.7 1064.84   164.4 1060.12   183.5 1044.12     193 1037.05   202.5 1031.87
   221.6 1023.18   231.1 1018.13   240.1 1014.61   250.1 1013.25   260.1 1014.22
   269.1 1014.46   307.2 1022.84   316.7  1025.6   346.4 1038.48   366.6 1047.99
   376.7 1051.39   386.8 1052.79     407 1063.01   447.3 1081.63   477.6  1097.9
   487.7  1100.2   497.8 1103.44   528.1 1119.62   588.7 1153.24   598.8  1153.9
#Mann= 3 , 0 , 0
       0      .1       0   240.1    .045       0   260.1      .1       0
Bank Sta=240.1,260.1
XS Rating Curve= 0 ,0
Exp/Cntr=0.3,0.1

Type RM Length L Ch R = 1 ,6039.5  ,286.8,299,311.3
XS GIS Cut Line= 4
     1699442.511      194773.953     1699399.943       194922.09
     1699376.104      195046.389     1699336.942      195243.906
#Sta/Elev= 30
     9.6 1127.54    28.9 1115.37    57.8 1096.16    67.4 1092.45    77.1  1089.3
   115.6 1063.29   144.5 1040.61   154.1 1033.41   163.9 1027.98   183.3 1023.35
   193.1 1018.45   202.8  1013.1   212.3 1009.43   222.3  1008.8   232.3 1010.45
     271 1019.93   280.7 1020.02   310.9  1026.7   341.1  1032.6   351.2 1035.26
   361.2 1038.72   371.3 1042.82   381.4 1043.95   391.4 1047.05   421.6 1061.83
   441.8 1072.51   451.9 1078.49   461.9 1085.28     472 1092.62   482.1 1096.73
#Mann= 3 , 0 , 0
       0      .1       0   212.3    .045       0   232.3      .1       0
Bank Sta=212.3,232.3
XS Rating Curve= 0 ,0
Exp/Cntr=0.3,0.1

Type RM Length L Ch R = 1 ,5740.4  ,182.6,194.6,206.6
XS GIS Cut Line= 4
     1699307.995      194692.222     1699164.966      194833.548
     1699047.478      194979.983     1698933.395      195114.498
#Sta/Elev= 30
    10.1 1128.71    30.2 1118.45    40.2  1116.2    50.3  1111.8    70.4 1099.68
    80.4 1093.05   100.5 1074.32   150.8 1035.84   170.9 1022.23     181 1019.55
   201.1 1010.32     211 1007.71   230.7 1006.09   260.4 1006.16   299.8 1001.74
   309.8 1001.09   319.8 1002.13   339.4 1010.06   359.2 1016.99   369.1 1021.41
   408.4 1042.12   418.2  1049.8     428 1055.16   437.8    1058   516.2 1097.69
     526  1106.5   535.8 1112.08   545.6 1116.59   555.4 1119.55   565.2 1124.36
#Mann= 3 , 0 , 0
       0     .06       0   299.8    .045       0   319.8     .06       0
Bank Sta=299.8,319.8
XS Rating Curve= 0 ,0
Exp/Cntr=0.3,0.1

Type RM Length L Ch R = 1 ,5545.9  ,138.5,135.5,132.6
XS GIS Cut Line= 4
     1699275.643      194564.517     1699115.587      194705.843
     1698938.503      194784.169     1698722.257      194974.874
#Sta/Elev= 30
     9.7 1158.02    48.5 1139.18    67.9 1124.07    87.3  1115.9   126.2 1092.56
   145.6 1079.99   155.3 1069.62     165 1061.94   203.8 1036.38   252.2 1011.68
     291  999.31   300.3  997.17   310.3  996.92   320.3  997.67   339.4 1000.86
   358.7 1002.62   378.1 1003.39   417.1 1002.69     427 1006.46   486.7 1044.37
   496.6 1051.07   506.6 1059.88   556.3 1091.58   576.2 1098.23   586.1 1104.67
     606  1121.4   635.8 1142.34   665.7 1162.16   685.5 1173.53   695.5 1181.44
#Mann= 3 , 0 , 0
       0     .06       0   300.3    .045       0   320.3     .06       0
Bank Sta=300.3,320.3
XS Rating Curve= 0 ,0
Exp/Cntr=0.3,0.1

Type RM Length L Ch R = 1 ,5410.3  ,137.1,136.9,136.5
XS GIS Cut Line= 4
     1699187.102      194447.029     1699049.181      194576.436
     1698863.583      194687.113     1698652.445      194767.142
#Sta/Elev= 30
      10 1156.66    49.8 1134.22    59.7 1126.52    69.7 1116.88    79.6 1111.46
    89.6 1107.68    99.5 1101.96   149.3 1070.87   169.2  1053.2   218.6  1022.9
   238.2 1014.93   248.1 1009.29   257.9 1004.74   277.5  996.47   287.2  993.59
   297.2  992.98   307.2  993.42   385.6  997.08   405.2  999.43     415 1003.66
   434.7 1010.35   454.3 1017.84   483.8 1030.54   493.6 1035.55   503.4 1043.95
   542.7 1063.46   552.5 1066.84   591.7 1077.68   621.2 1084.03     631 1084.56
#Mann= 3 , 0 , 0
       0     .06       0   287.2    .045       0   307.2     .06       0
Bank Sta=287.2,307.2
XS Rating Curve= 0 ,0
Exp/Cntr=0.3,0.1

Type RM Length L Ch R = 1 ,5273.5  ,131.2,130.6,130
XS GIS Cut Line= 4
     1699141.128      194349.973     1698970.855      194464.056
      1698786.96      194576.436      1698637.12      194727.979
#Sta/Elev= 30
     9.8 1149.83    19.5 1142.73    48.8  1128.6    87.8 1108.02   107.4 1090.84
   146.4 1068.37   175.7 1052.12   185.4 1043.43   195.2 1037.05   234.3  1015.9
   253.9 1009.92   263.7    1006   273.5 1000.45   283.3  997.15   302.7  989.47
   312.7  987.44   322.7  987.72   351.9  991.93   371.5  995.82   381.3  999.19
   410.7 1015.33   420.5 1019.04   439.8 1024.33   459.2 1030.37     498 1034.91
   517.3 1038.55   556.1 1050.52   575.5 1059.54   585.2 1063.28   633.6 1075.73
#Mann= 3 , 0 , 0
       0     .08       0   302.7    .045       0   322.7     .08       0
Bank Sta=302.7,322.7
XS Rating Curve= 0 ,0
Exp/Cntr=0.3,0.1

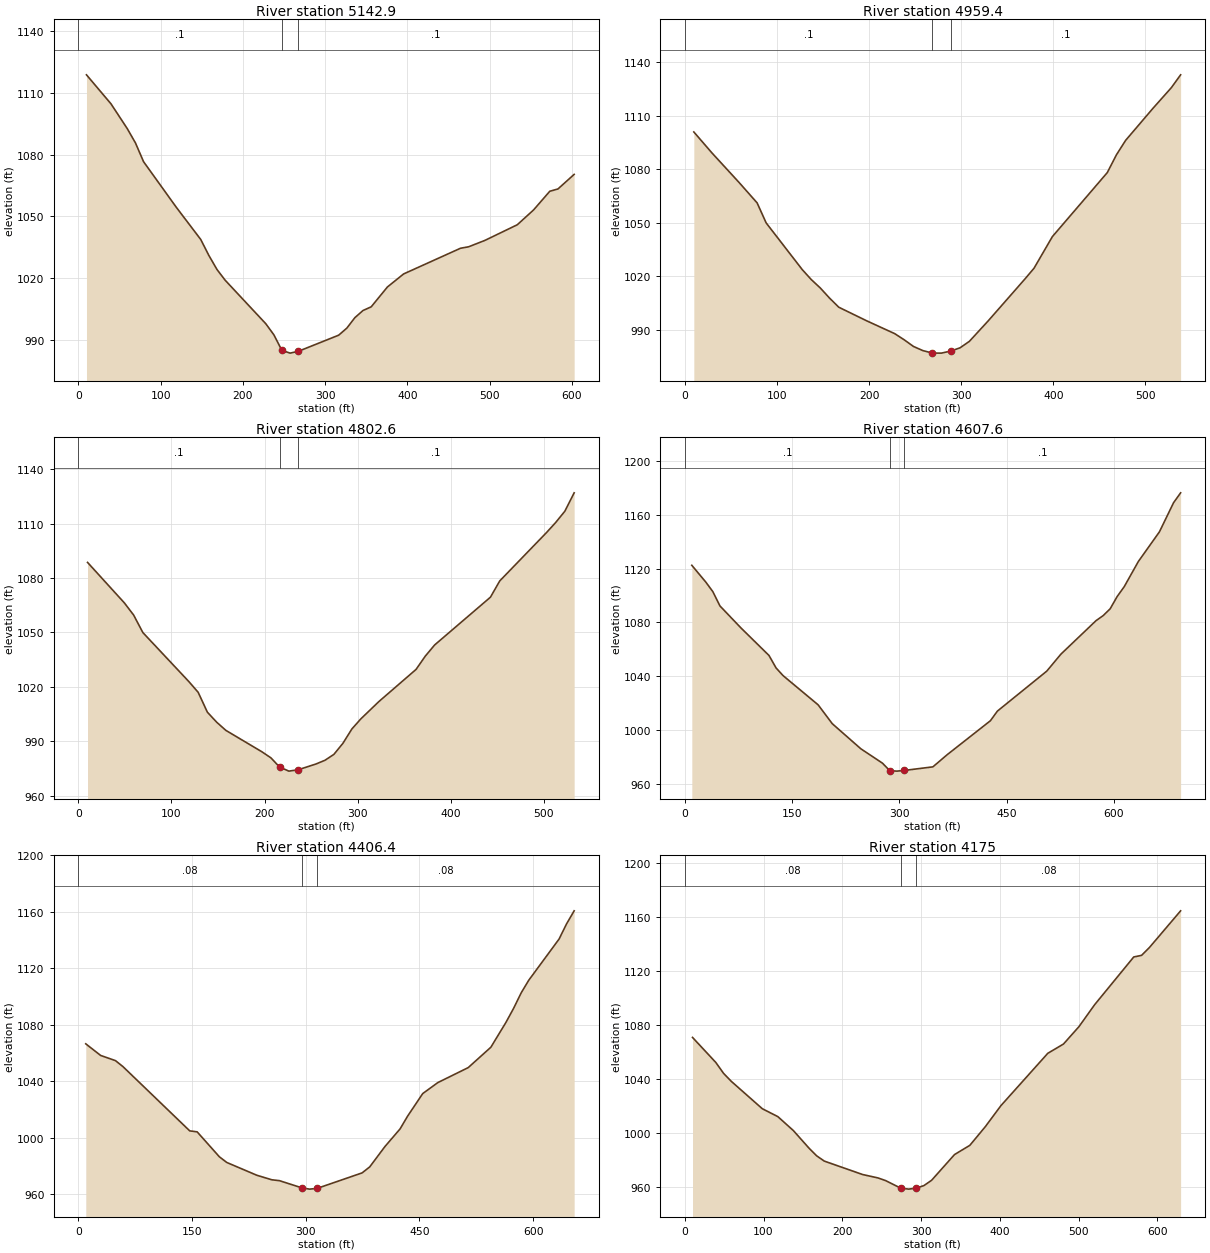
Type RM Length L Ch R = 1 ,5142.9  ,170.1,183.5,196.8
XS GIS Cut Line= 4
      1699030.45      194268.242      1698880.61      194365.298
     1698756.311      194445.326     1698608.174        194678.6
#Sta/Elev= 30
     9.9 1118.84    39.7 1104.74    59.5 1092.69    69.4 1085.77    79.3 1076.62
     119 1054.52   148.8 1038.82   158.7 1031.04   168.6  1024.2   178.5 1019.01
   227.8  997.91   237.7  992.49   247.4  984.95   257.4  983.59   267.4  984.47
   316.5  992.32   326.4  995.75   336.2 1000.84   346.1 1004.32     356 1006.09
   375.7 1015.73   395.4 1022.07   464.5 1034.55   474.4 1035.27   494.1 1038.35
   533.6 1045.98   553.4 1053.19   573.1 1062.26     583 1063.37   602.7 1070.46
#Mann= 3 , 0 , 0
       0      .1       0   247.4    .045       0   267.4      .1       0
Bank Sta=247.4,267.4
XS Rating Curve= 0 ,0
Exp/Cntr=0.3,0.1

Type RM Length L Ch R = 1 ,4959.4  ,153.2,156.8,160.5
XS GIS Cut Line= 4
     1698969.152       194217.16     1698817.609      194258.026
     1698635.418      194266.539     1698444.712      194322.729
#Sta/Elev= 30
     9.8  1100.9    29.4 1089.18    58.9 1072.56    78.5  1061.1    88.3 1049.88
   127.5 1023.66   137.3 1018.07   147.1 1013.34     157 1007.75   167.1 1002.57
   197.5  994.91   227.9  987.72     238  984.33   248.2  980.55   258.3  978.24
   268.6  976.85   278.5   976.8   288.6  977.95   298.8  979.79   308.9  983.41
   329.2  994.82   369.2  1018.4   379.1 1024.46     399 1042.17   458.6  1078.1
   468.6 1088.13   478.5 1096.17   508.3 1114.23   528.2 1125.78   538.2 1132.95
#Mann= 3 , 0 , 0
       0      .1       0   268.6    .045       0   288.6      .1       0
Bank Sta=268.6,288.6
XS Rating Curve= 0 ,0
Exp/Cntr=0.3,0.1

Type RM Length L Ch R = 1 ,4802.6  ,206.4,195,183.5
XS GIS Cut Line= 4
     1698940.206      194121.808     1698781.852      194116.699
      1698618.39      194099.672     1698425.982      194183.106
#Sta/Elev= 30
     9.9 1088.58    49.5 1066.23    59.4 1059.56    69.3 1049.92   118.8 1022.84
   128.7 1016.98   138.6 1006.03   148.5 1000.55   158.4  996.02   197.1  984.21
   206.8  980.87   216.1  975.81   226.1  973.54   236.1  974.29   255.1  977.45
   264.8   979.5   274.4  982.74   284.1  988.83   293.8  996.79   303.4 1002.33
   322.8 1011.89   362.7  1029.6   372.7 1036.97   382.7 1043.09   442.6 1069.41
   452.6 1078.38   502.5 1104.86   512.5 1110.48   522.5 1116.79   532.5 1126.93
#Mann= 3 , 0 , 0
       0      .1       0   216.1    .045       0   236.1      .1       0
Bank Sta=216.1,236.1
XS Rating Curve= 0 ,0
Exp/Cntr=0.3,0.1

Type RM Length L Ch R = 1 ,4607.6  ,218.3,201.2,184.2
XS GIS Cut Line= 4
     1698981.071      193914.075     1698766.528      193890.236
     1698577.525      193960.048     1698322.116      194063.915
#Sta/Elev= 30
     9.8 1122.43    29.4 1109.92    39.2 1102.84    49.1 1092.22    78.5 1075.83
   117.7 1055.34   127.6 1046.06   137.4 1040.34   186.4  1018.6   206.1 1004.61
   246.1   985.9   276.3  975.21   286.5  969.63   296.5  969.28   306.5  969.77
   346.8  972.46     367   981.6   427.2 1006.77     437 1013.95     506 1043.69
   525.7 1056.29   574.9 1081.26   584.8 1084.98   594.6 1090.07   604.4  1099.2
   614.3 1106.56     634 1125.25   663.5 1147.34   683.2 1168.97   693.1 1176.36
#Mann= 3 , 0 , 0
       0      .1       0   286.5    .045       0   306.5      .1       0
Bank Sta=286.5,306.5
XS Rating Curve= 0 ,0
Exp/Cntr=0.3,0.1

Type RM Length L Ch R = 1 ,4406.4  ,228.5,231.4,234.2
XS GIS Cut Line= 4
     1698706.932      193495.203     1698621.796      193682.504
     1698534.957      193827.235     1698327.224      194014.536
#Sta/Elev= 30
     9.8 1066.49    29.4 1058.27      49 1054.59    58.8  1050.4     147 1004.87
   156.8 1004.17   186.1  986.53   195.9   982.5   235.5  973.46   255.4  970.24
   265.3  969.64     295  964.53     305  963.64     315  964.14   374.5  975.15
   384.5   979.4   404.5  993.75   424.5 1006.25   434.5 1015.33   454.4 1031.27
   474.4 1039.07   514.4 1049.64   544.3 1064.07   564.3 1081.74   574.3 1091.59
   584.3 1102.54   594.3 1111.49   634.3 1140.64   644.2  1151.4   654.2 1160.62
#Mann= 3 , 0 , 0
       0     .08       0     295    .045       0     315     .08       0
Bank Sta=295,315
XS Rating Curve= 0 ,0
Exp/Cntr=0.3,0.1

Type RM Length L Ch R = 1 ,4175    ,167.5,167.2,166.9
XS GIS Cut Line= 4
     1698545.173      193425.392      1698431.09      193573.529
      1698318.71      193719.964     1698189.303      193943.021
#Sta/Elev= 30
     9.8 1070.85    39.4 1052.25    49.2 1044.18      59 1038.27    98.4 1017.93
   118.1 1012.08   137.8 1001.74   157.5  988.79   167.3  983.03   177.1  979.07
   225.8   969.1   245.3  966.58     255  964.59   274.1  959.01   284.1  958.28
   294.1  959.05   303.6  960.93   313.3  964.85   342.4  983.93   361.8  990.75
   381.5 1004.63   401.3 1020.23   460.8 1059.06   480.7 1065.93   500.5 1078.94
   520.3 1095.15   569.9 1130.54   579.8 1131.72   589.8 1137.55   629.4 1164.77
#Mann= 3 , 0 , 0
       0     .08       0   274.1    .045       0   294.1     .08       0
Bank Sta=274.1,294.1
XS Rating Curve= 0 ,0
Exp/Cntr=0.3,0.1

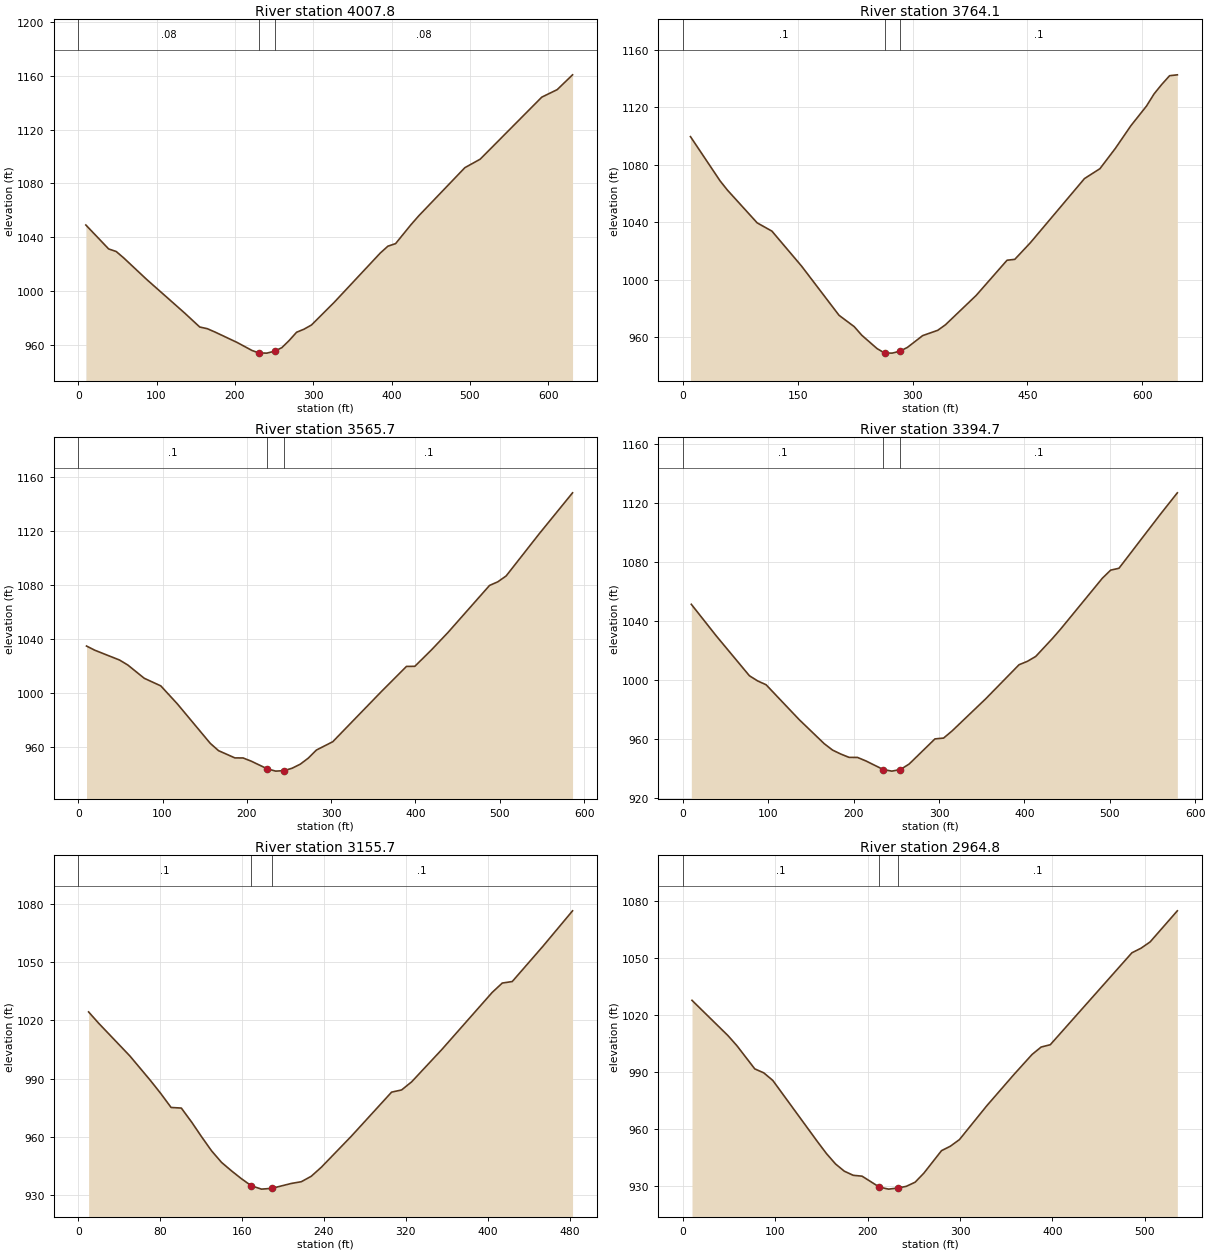
Type RM Length L Ch R = 1 ,4007.8  ,251.3,243.7,236.2
XS GIS Cut Line= 4
     1698383.414      193365.796     1698274.439      193502.014
     1698189.303      193616.097     1698088.842      193914.075
#Sta/Elev= 30
     9.7 1049.11    38.8  1031.3    48.5 1029.37    58.1 1024.58    87.2 1008.68
   135.7  983.67   155.1   973.2   164.8  971.93   174.4  969.51   202.9  961.68
   221.9  955.71   230.9  953.86   240.9  953.75   250.9  955.26   259.9  957.78
   269.3  963.13   278.8  969.29   288.3  971.57   297.8  974.68   326.6  991.41
   385.6 1028.19   395.4 1033.34   405.2 1035.24   424.9 1049.36   434.7 1055.87
   493.7 1091.78   513.3 1098.11   591.9 1144.26   611.6 1149.85   631.2 1160.87
#Mann= 3 , 0 , 0
       0     .08       0   230.9    .045       0   250.9     .08       0
Bank Sta=230.9,250.9
XS Rating Curve= 0 ,0
Exp/Cntr=0.3,0.1

Type RM Length L Ch R = 1 ,3764.1  ,205,198.4,191.7
XS GIS Cut Line= 4
      1698131.41      193169.982     1698061.598      193340.255
     1698002.002      193508.825     1697918.569      193779.559
#Sta/Elev= 30
     9.7 1099.61    48.4 1068.79    58.1  1062.3    96.9 1039.52   116.2 1033.76
     155 1009.35   203.9  975.13   223.8   967.2   233.7   961.2   253.6  951.94
   263.4  948.84   273.4  948.77   283.4   950.1   293.3  952.77   313.2  960.97
     333  964.69     343  968.52   383.1  988.94   423.5 1013.48   433.6  1014.1
   453.9 1025.62   524.7 1070.37   544.9 1077.26   565.2 1091.51   585.4 1107.22
   605.7 1120.85   615.8 1129.45   625.9 1136.08     636 1142.05   646.1 1142.66
#Mann= 3 , 0 , 0
       0      .1       0   263.4    .045       0   283.4      .1       0
Bank Sta=263.4,283.4
XS Rating Curve= 0 ,0
Exp/Cntr=0.3,0.1

Type RM Length L Ch R = 1 ,3565.7  ,171.5,171,170.5
XS GIS Cut Line= 4
     1697864.081      193159.766     1697843.649      193324.931
     1697828.324      193527.555     1697797.675      193742.099
#Sta/Elev= 30
     9.8 1034.94    19.6 1031.86    48.9 1024.62    58.7 1020.96    78.3 1011.12
    97.9 1005.51   117.5  992.25   156.6  963.05   166.4  957.66   185.8  952.31
   195.5  952.27   205.1  949.92   224.2  944.24   234.2  942.54   244.2  942.91
   253.5  944.65   263.2  947.61   272.9  952.17   282.5  958.12   301.9  964.27
     360 1001.61   389.3 1019.89   399.2 1019.96   418.9 1032.06   438.6    1045
   487.8 1079.69   497.7 1082.41   507.5 1086.71   546.9 1117.97   586.3 1148.12
#Mann= 3 , 0 , 0
       0      .1       0   224.2    .045       0   244.2      .1       0
Bank Sta=224.2,244.2
XS Rating Curve= 0 ,0
Exp/Cntr=0.3,0.1

Type RM Length L Ch R = 1 ,3394.7  ,244.5,239,233.5
XS GIS Cut Line= 4
     1697666.565      193139.333      1697669.97      193343.661
     1697663.159      193464.554     1697664.862      193718.261
#Sta/Elev= 30
     9.7 1051.46    38.9 1030.07    77.8 1003.01    87.6  999.46    97.3  996.93
   136.2  973.22   165.4  956.98   175.2  952.63   184.9  949.92   194.6  947.67
   204.4  947.65   214.4  945.24   234.7  939.41   244.7  938.36   254.7  939.44
   264.9  943.15   295.2  960.21   305.3  960.77   315.4  965.69   354.7  987.42
   393.7 1010.48   403.5  1012.8   413.3 1016.13   432.8 1028.24   442.5 1034.69
   491.3 1069.12   501.1 1074.63   510.8 1075.89   559.6 1112.71   579.2 1127.04
#Mann= 3 , 0 , 0
       0      .1       0   234.7    .045       0   254.7      .1       0
Bank Sta=234.7,254.7
XS Rating Curve= 0 ,0
Exp/Cntr=0.3,0.1

Type RM Length L Ch R = 1 ,3155.7  ,186.1,190.9,195.7
XS GIS Cut Line= 4
     1697423.075       193212.55     1697417.966      193323.228
     1697440.102      193457.743     1697499.697      193685.909
#Sta/Elev= 30
    10.1 1024.33    20.1 1018.41    50.4 1001.68    70.5  989.05    80.6  982.34
    90.7  975.14   100.7  974.84   110.8   967.6   120.5  960.06   130.3  952.78
     140  946.87   149.7  942.52   159.5  938.44     169  934.86     179  933.11
     189   933.5   208.2  936.04   217.9  936.92   227.6  939.72   237.4  944.34
   266.8  960.36   306.1  983.03   315.9  984.17   325.7  988.34   355.2 1004.98
   404.3 1034.31   414.2 1039.18     424 1039.98   453.5 1057.84   482.9 1076.37
#Mann= 3 , 0 , 0
       0      .1       0     169    .045       0     189      .1       0
Bank Sta=169,189
XS Rating Curve= 0 ,0
Exp/Cntr=0.3,0.1

Type RM Length L Ch R = 1 ,2964.8  ,171,173.3,175.5
XS GIS Cut Line= 3
     1697244.288       193212.55     1697240.883      193502.014
      1697257.91      193747.207
#Sta/Elev= 30
     9.7 1027.63    48.6 1009.07    58.3 1003.75    77.7  991.49    87.4  989.41
    97.2  985.42   145.7  953.05   155.4   946.8   165.2  941.35   174.7  937.55
   184.3   935.4   193.9  934.94   212.6  929.18   222.6  928.11   232.6  928.69
   241.7  929.57   251.3  931.75   260.8  936.53   279.9  948.38   289.5  950.73
   299.3  954.21   328.8  971.98   358.3  988.51     378  999.11   387.8 1003.01
   397.7 1004.23   486.1  1052.7     496 1055.12   505.8 1058.42   535.3 1074.82
#Mann= 3 , 0 , 0
       0      .1       0   212.6    .045       0   232.6      .1       0
Bank Sta=212.6,232.6
XS Rating Curve= 0 ,0
Exp/Cntr=0.3,0.1

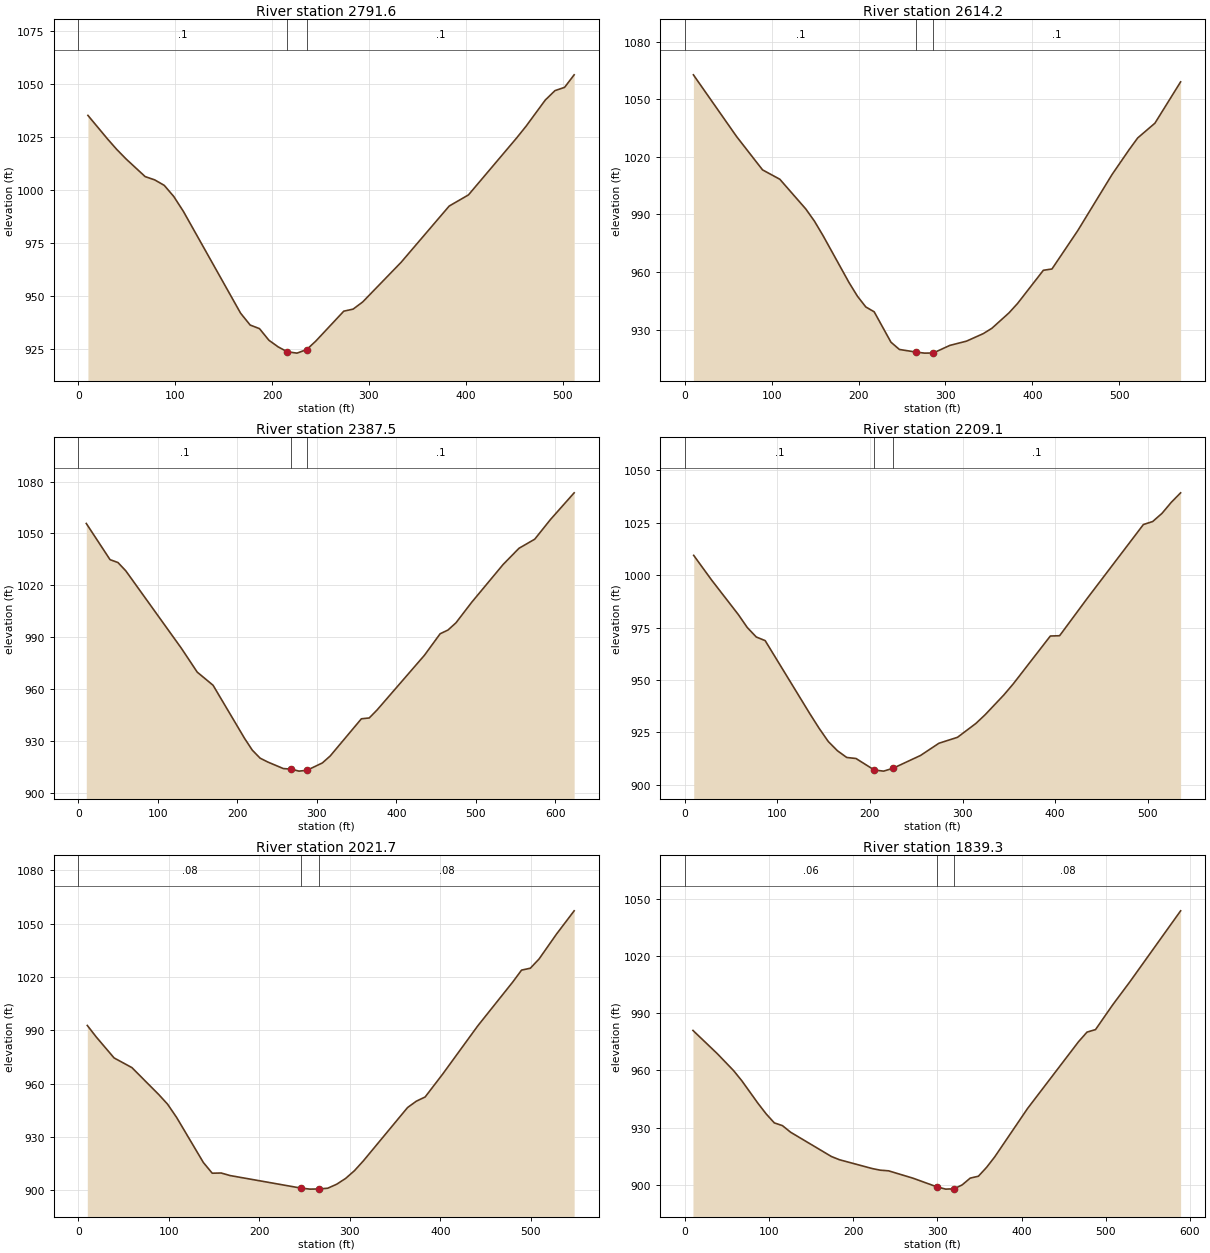
Type RM Length L Ch R = 1 ,2791.6  ,183.5,177.3,171.1
XS GIS Cut Line= 4
     1697085.935      193200.631     1697075.718      193377.715
     1697063.799      193483.284     1697060.393       193711.45
#Sta/Elev= 30
     9.9 1035.08    29.6 1024.28    39.4 1019.18    49.3 1014.56      69 1006.26
    78.8 1004.73    88.7 1002.14    98.5  996.91   108.4  989.93   167.5  941.96
   177.4  936.37     187  934.69   196.7  929.23   206.4  926.06   215.7  923.79
   225.7  923.16   235.7  924.84     245  928.77     274  942.91   283.6  943.87
   293.5  947.24   333.2  965.93   382.8   992.4   402.7  997.65   452.3 1024.39
   462.2 1030.01     482 1042.31     492 1046.74   501.9 1048.28   511.8 1054.18
#Mann= 3 , 0 , 0
       0      .1       0   215.7    .045       0   235.7      .1       0
Bank Sta=215.7,235.7
XS Rating Curve= 0 ,0
Exp/Cntr=0.3,0.1

Type RM Length L Ch R = 1 ,2614.2  ,223.6,226.7,229.7
XS GIS Cut Line= 3
     1696881.607      193158.063      1696902.04      193500.312
     1696944.608      193723.369
#Sta/Elev= 30
     9.9 1062.66    59.7 1030.49    89.5 1013.19   109.4  1008.3   139.3  992.82
   149.2  986.52   159.2  978.91     189  954.57   198.7  947.44   208.3  941.86
     218  939.31   237.3   923.5     247  919.72     266  918.36     276  917.81
     286  917.88     305  921.82   324.3  924.06   343.6  927.97   353.5  930.75
   373.2  938.78   383.1   943.7   412.7  960.93   422.6   961.6   452.2   981.5
   491.7 1010.72   511.4 1023.68   521.3 1029.81   541.1 1037.48   570.7    1059
#Mann= 3 , 0 , 0
       0      .1       0     266    .045       0     286      .1       0
Bank Sta=266,286
XS Rating Curve= 0 ,0
Exp/Cntr=0.3,0.1

Type RM Length L Ch R = 1 ,2387.5  ,183.5,178.4,173.4
XS GIS Cut Line= 4
     1696655.144      193190.415     1696668.766      193379.418
     1696670.469      193536.069      1696677.28      193813.614
#Sta/Elev= 30
      10 1055.77    39.9 1034.87    49.9 1033.19    59.8 1028.36   129.7  983.65
   149.6   969.9   169.5  962.33   209.1  931.68   218.9  924.83   228.7  920.22
   238.4  917.98     258   914.2   267.6   913.9   277.6  912.73   287.6   913.2
     307  917.46   316.8  921.44   356.1  942.95     366  943.44   375.9  948.08
   435.4  979.62   455.2  992.06   465.1  994.23   475.1  998.39   494.9 1010.25
   534.5 1032.11   554.4 1041.43   574.2 1046.68     594 1058.05   623.8 1073.46
#Mann= 3 , 0 , 0
       0      .1       0   267.6    .045       0   287.6      .1       0
Bank Sta=267.6,287.6
XS Rating Curve= 0 ,0
Exp/Cntr=0.3,0.1

Type RM Length L Ch R = 1 ,2209.1  ,188.6,187.4,186.3
XS GIS Cut Line= 4
     1696464.439       193250.01     1696476.358      193384.526
     1696513.818      193559.907     1696559.791      193776.154
#Sta/Elev= 30
     9.6 1009.43    28.9   997.7    57.9  981.15    67.5  975.01    77.2   970.5
    86.8  968.77     135  933.96     145  927.01     155  920.65   164.9  916.24
   174.9  913.05   184.9  912.56   204.7  907.06   214.7  906.54   224.7  907.86
   254.6  914.01   274.5  919.84   294.5  922.66   314.4  929.28   324.4  933.44
   344.5  942.83   354.6  948.07   394.8  970.97   404.8  971.11     435  989.13
   495.3 1024.13   505.3 1025.56   515.4 1029.46   525.4 1034.72   535.5 1039.25
#Mann= 3 , 0 , 0
       0      .1       0   204.7    .045       0   224.7      .1       0
Bank Sta=204.7,224.7
XS Rating Curve= 0 ,0
Exp/Cntr=0.3,0.1

Type RM Length L Ch R = 1 ,2021.7  ,186.3,182.3,178.4
XS GIS Cut Line= 4
     1696256.706      193260.227     1696287.355      193404.959
     1696340.139      193604.178     1696418.465      193781.262
#Sta/Elev= 30
     9.9  992.72    19.7  986.29    39.5  974.44    59.2  968.99    88.8  953.86
    98.6   948.4   108.5  941.02   138.1  915.61   147.9  909.58   157.8  909.69
   167.6  908.26   245.9   901.2   255.9  900.62   265.9  900.71   275.5  901.13
   285.3  903.35   295.2  906.61     305  910.99   314.8  916.49   363.7  946.54
   373.4  950.11   383.1  952.47   402.4  965.31   441.2  992.46   479.9 1017.18
   489.6 1023.85   499.3 1024.92   508.9 1030.09   528.3 1044.19   547.7 1057.21
#Mann= 3 , 0 , 0
       0     .08       0   245.9    .045       0   265.9     .08       0
Bank Sta=245.9,265.9
XS Rating Curve= 0 ,0
Exp/Cntr=0.3,0.1

Type RM Length L Ch R = 1 ,1839.3  ,230.8,235.1,239.4
XS GIS Cut Line= 4
     1696006.978      193291.231     1696091.541      193454.338
     1696181.785      193658.665     1696306.085      193791.478
#Sta/Elev= 30
     9.7  980.95    38.7  968.74      58  959.89    67.7  954.62      87  942.74
    96.7  937.21   106.4  932.52     116   931.1   125.7  927.64   174.1  914.94
   183.7  913.24   222.6  908.62   232.3  907.76     242  907.43   271.1  903.57
     300  898.95     310  897.84     320  898.02   329.4  900.03   339.1  903.61
   348.8   904.6   358.5  909.24   368.2  914.75   407.1  940.03   467.7  975.03
   477.8  980.07   487.9  981.39   508.2  994.29   528.4 1006.23     589 1043.59
#Mann= 3 , 0 , 0
       0     .06       0     300    .045       0     320     .08       0
Bank Sta=300,320
XS Rating Curve= 0 ,0
Exp/Cntr=0.3,0.1