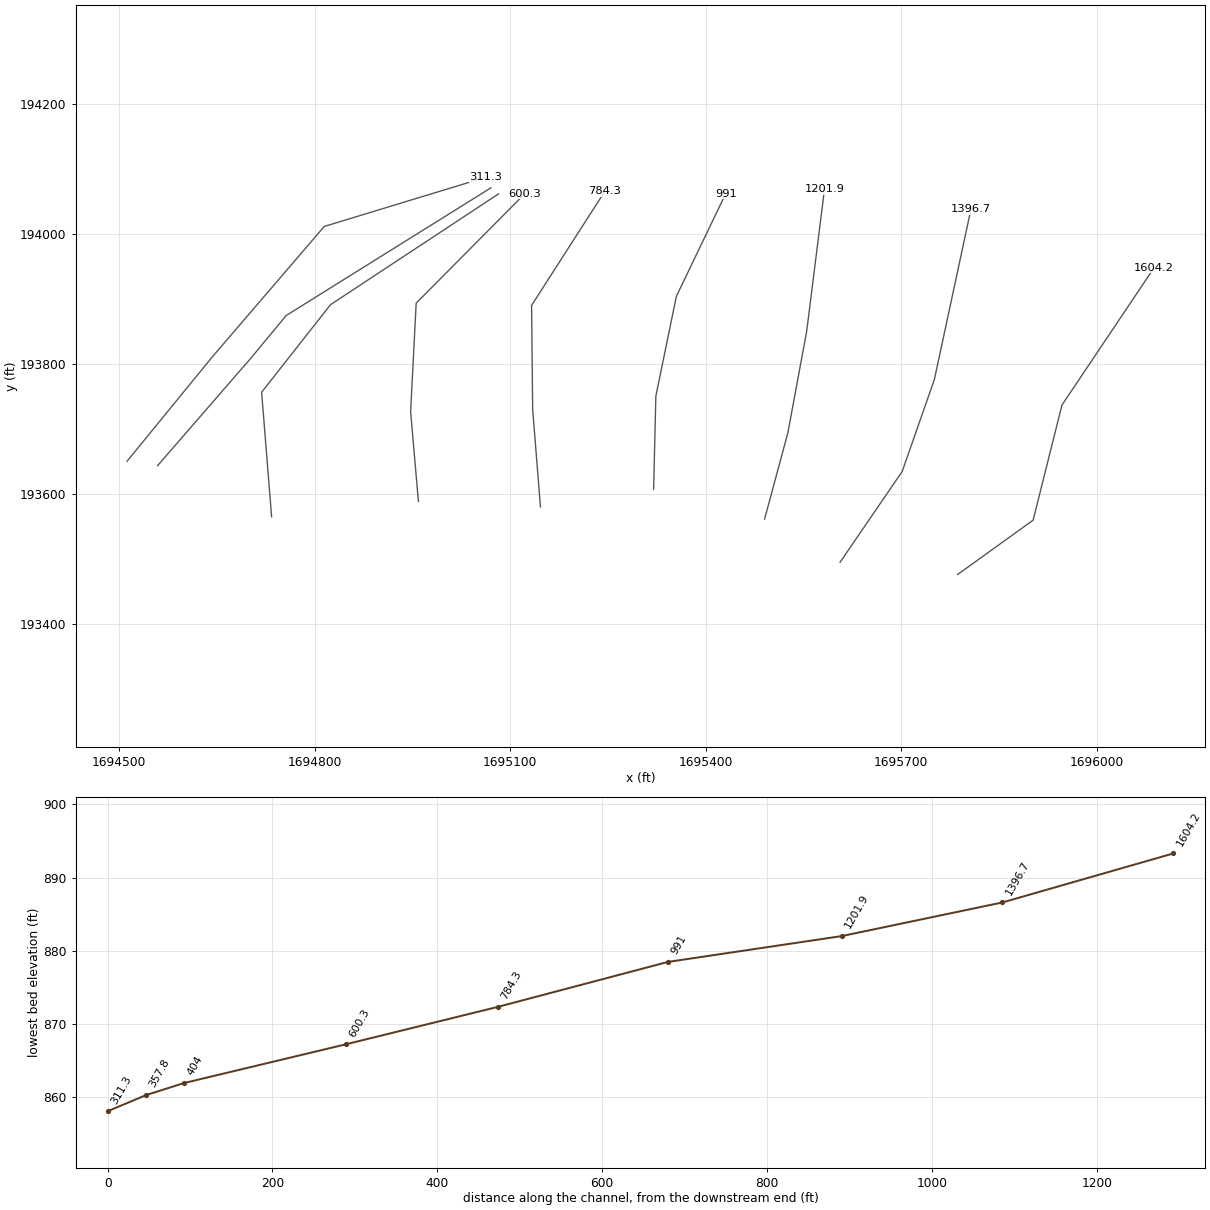
HEC-RAS study trkycrk1.prj: trkycrk1

--- trkycrk1.g01 (geometry) --- (continued)

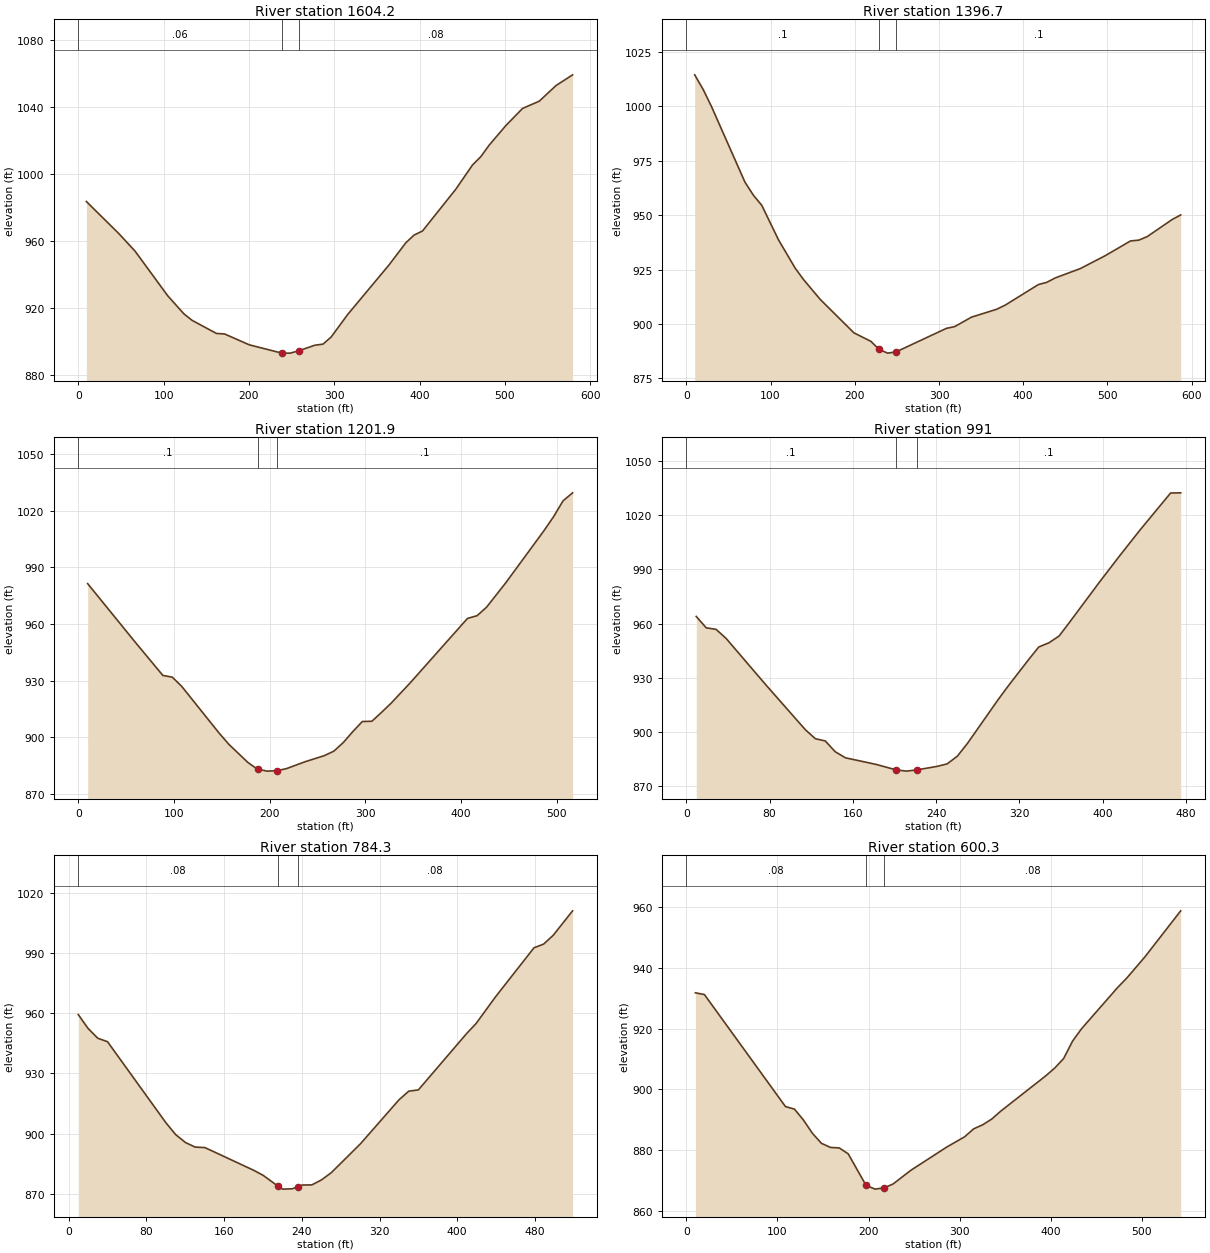
Type RM Length L Ch R = 1 ,1604.2  ,209.8,207.6,205.3
XS GIS Cut Line= 4
     1695786.753      193476.473     1695902.538      193559.907
     1695946.809      193736.991     1696088.135      193948.129
#Sta/Elev= 30
     9.5  983.61    47.6  964.48    66.6  954.03   104.7  927.56   123.7  916.74
   133.2  912.89   161.9  905.03   171.5  904.71   200.4  898.24   238.4  893.34
   238.8   893.3   248.4   893.3   258.4  894.69   277.2     898   286.8  898.65
   296.4   902.9   315.6  916.23   364.3  945.91   383.9  959.03   393.7  963.67
   403.4  966.04   442.5  990.97   462.1 1005.43   471.8 1010.36   481.6 1017.22
   501.1 1028.85   520.7 1039.06   540.2 1043.35   559.8 1052.64   579.3 1059.06
#Mann= 3 , 0 , 0
       0     .06       0   238.4    .045       0   258.4     .08       0
Bank Sta=238.4,258.4
XS Rating Curve= 0 ,0
Exp/Cntr=0.3,0.1

Type RM Length L Ch R = 1 ,1396.7  ,190.9,194.8,198.6
XS GIS Cut Line= 4
     1695606.263      193495.203     1695701.616      193634.827
     1695750.995      193776.154     1695807.185      194038.374
#Sta/Elev= 30
     9.9 1014.52    19.9 1007.84    29.8  999.98    69.6  965.18    79.6  959.18
    89.5  954.57   109.4  938.69   129.3  925.61   139.2  920.39   159.1  911.23
     199  895.92     219  892.04   228.9  888.34   238.9   886.6   248.9  887.15
   308.8  897.98   318.8  898.82   338.6  903.14   368.4  906.75   378.4  908.61
   418.1  918.13     428  919.14     438  921.16   467.8  925.46   497.6  931.43
   527.4  938.16   537.3  938.54   547.2  940.15     577  948.05     587  950.13
#Mann= 3 , 0 , 0
       0      .1       0   228.9    .045       0   248.9      .1       0
Bank Sta=228.9,248.9
XS Rating Curve= 0 ,0
Exp/Cntr=0.3,0.1

Type RM Length L Ch R = 1 ,1201.9  ,211.4,210.9,210.4
XS GIS Cut Line= 4
     1695490.478       193561.61     1695526.235      193694.423
     1695555.181      193851.074     1695582.425      194069.023
#Sta/Elev= 30
     9.8  981.43    58.9  950.77    88.4  932.74    98.2  931.85   108.1  926.95
   147.5  901.97   157.5  896.15   177.4  886.53   187.3  883.05   197.3  882.01
   207.3  882.23   217.2  883.27   237.1  887.01     257   890.2     267  892.58
   276.9  897.15   286.9  902.99   296.8  908.31   306.8  908.45   316.8  913.13
   326.8  917.99   346.8   928.8   406.7  962.98   416.7  964.42   426.6  968.92
   446.6  981.81   486.5 1009.43   496.5  1016.8   506.5 1025.29   516.5 1029.56
#Mann= 3 , 0 , 0
       0      .1       0   187.3    .045       0   207.3      .1       0
Bank Sta=187.3,207.3
XS Rating Curve= 0 ,0
Exp/Cntr=0.3,0.1

Type RM Length L Ch R = 1 ,991     ,201.4,206.7,212
XS GIS Cut Line= 4
     1695320.205      193607.583      1695323.61      193750.613
     1695355.051      193904.045     1695430.882      194062.212
#Sta/Elev= 30
     9.5  963.93    19.1  957.65    28.6  956.79    38.2  951.81    76.3  926.21
   114.5  901.28     124  896.38   133.5  895.16   143.1  889.18   152.9  885.84
   182.2  882.22   201.6  879.17   211.6  878.48   221.6  879.17     241   881.1
   250.7   882.5   260.5  886.77   270.3  893.91   299.7  918.02   309.4  925.56
   328.9  940.07   338.7  947.07   348.4  949.35   358.2  953.11   367.9  960.41
   397.1  982.96   416.6  997.56   436.1 1011.75   465.4 1032.12   475.1 1032.23
#Mann= 3 , 0 , 0
       0      .1       0   201.6    .045       0   221.6      .1       0
Bank Sta=201.6,221.6
XS Rating Curve= 0 ,0
Exp/Cntr=0.3,0.1

Type RM Length L Ch R = 1 ,784.3   ,185.6,184,182.5
XS GIS Cut Line= 4
     1695146.527       193580.34     1695134.607       193730.18
     1695132.905      193890.236     1695245.285      194065.617
#Sta/Elev= 30
      10  959.29      20  952.43    30.1  947.48    40.1  945.77   100.2   905.4
   110.2   899.5   120.3  895.56   130.3  893.27   140.3  893.03   190.3  881.77
   200.3  879.19   215.9  873.67   220.3  872.33   230.3   872.5     236  873.55
   240.4  874.37   250.4  874.43   260.4  876.96   270.4  880.53   300.4  894.92
   340.1  916.84   350.1  921.12     360  921.76   409.6   949.8   419.5  954.89
   439.3  968.05     479  992.55   488.9  994.38   498.8  998.79   518.7 1010.95
#Mann= 3 , 0 , 0
      10     .08       0   215.9    .045       0     236     .08       0
Bank Sta=215.9,236
XS Rating Curve= 0 ,0
Exp/Cntr=0.3,0.1

Type RM Length L Ch R = 1 ,600.3   ,211.9,196.3,180.6
XS GIS Cut Line= 4
     1694959.226      193588.853     1694947.307      193726.774
     1694955.821      193893.642     1695122.688      194062.212
#Sta/Elev= 30
     9.9  931.78    19.8  931.22   108.8  894.38   118.7  893.54   128.5  889.97
   138.4  885.58   148.3  882.29   158.1  880.95   167.9  880.77   177.7  878.83
   197.2   868.5   207.2  867.23   217.2  867.67   226.9  868.91   246.5  873.43
   285.9  881.07   305.5  884.44   315.4  887.05   325.3  888.38   335.2  890.25
   345.1  892.86   394.5  904.47   404.4  907.04   414.2  910.18   424.1  915.96
     434  920.02   473.5  933.54   483.4  936.59   503.2  943.52   542.7  958.74
#Mann= 3 , 0 , 0
       0     .08       0   197.2    .045       0   217.2     .08       0
Bank Sta=197.2,217.2
XS Rating Curve= 0 ,0
Exp/Cntr=0.3,0.1

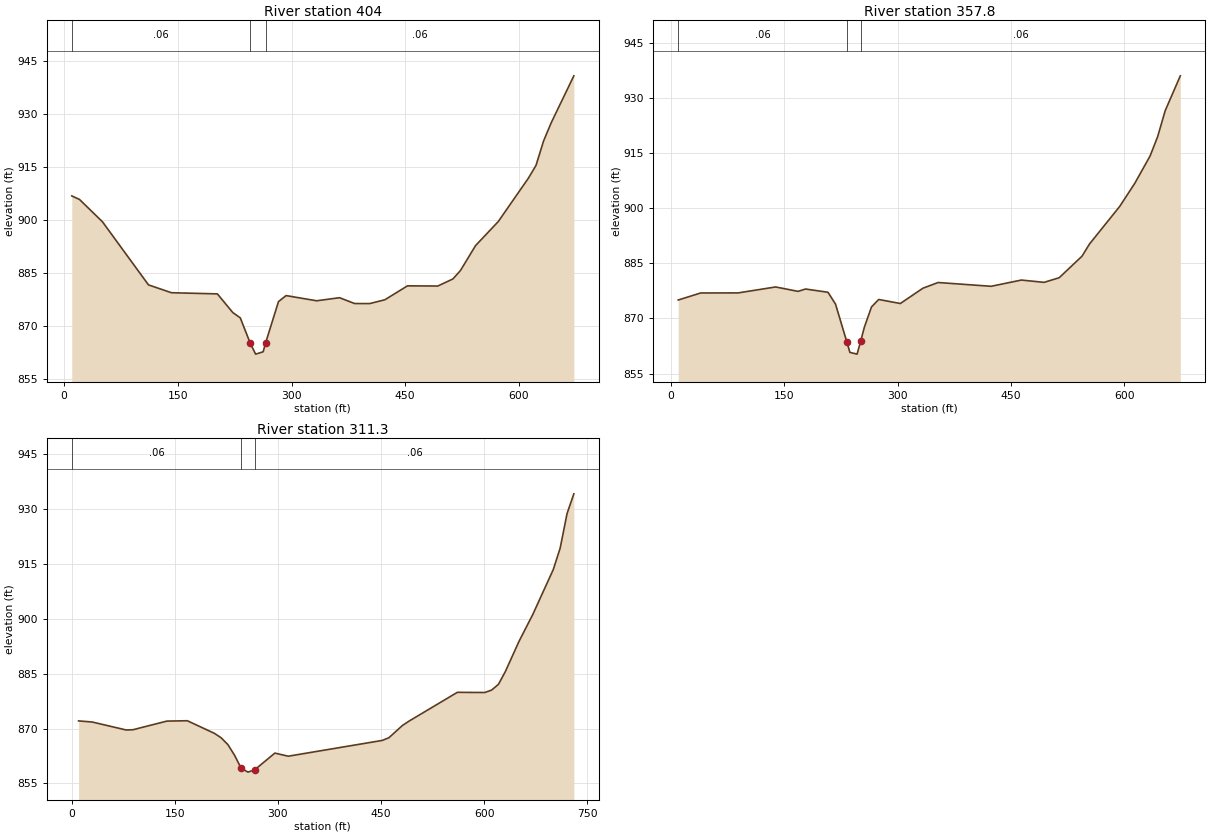
Type RM Length L Ch R = 1 ,404     ,46.7,46.2,45.8
XS GIS Cut Line= 4
     1694733.987      193565.122     1694718.663      193756.679
     1694824.338      193891.287     1695082.195       194061.68
#Sta/Elev= 30
    10.1  906.72    20.2  905.74    50.6   899.4   111.3  881.54   141.6  879.32
   202.2  878.99   222.4  873.73   232.4   872.2  245.57  865.01   252.6  861.94
   262.6   862.6  265.76  865.09   282.8  876.81   292.8  878.51   333.1  877.04
   363.3  877.91   383.2  876.26   403.2  876.25   423.1  877.32     453  881.27
   492.9  881.21   512.9  883.22   522.8   885.6   542.8  892.67   572.7  899.46
   612.6  911.79   622.5  915.36   632.5  922.29   642.5  927.41   672.4  940.71
#Mann= 3 , 0 , 0
    10.1     .06       0  245.57    .045       0  265.76     .06       0
Bank Sta=245.57,265.76
XS Rating Curve= 0 ,0
Exp/Cntr=0.3,0.1

Type RM Length L Ch R = 1 ,357.8   ,46.8,46.5,46.2
XS GIS Cut Line= 4
     1694559.032       193643.82     1694701.742      193808.559
     1694756.336      193874.646     1695070.489      194070.992
#Sta/Elev= 30
     9.9  875.03    39.6  876.95    89.2  876.97   138.7  878.59   168.4  877.39
   178.3  878.03     208  877.14     218  873.91  232.89  863.65     237  860.76
   246.5  860.29  251.27  863.81   256.1  867.61   265.6  873.15   275.1  875.18
   303.7  874.08   333.7  878.26   353.7   879.8   423.8  878.77   463.9  880.47
   493.9  879.84   513.9  881.11     544  886.96     554   890.3     594  900.55
   614.1   906.9   634.1  914.27   644.1  919.52   654.1  926.61   674.1  936.11
#Mann= 3 , 0 , 0
     9.9     .06       0  232.89    .045       0  251.27     .06       0
Bank Sta=232.89,251.27
XS Rating Curve= 0 ,0
Exp/Cntr=0.3,0.1

Type RM Length L Ch R = 1 ,311.3   ,323.1,311.3,299.5
XS GIS Cut Line= 4
     1694512.101      193650.524     1694643.317      193811.432
     1694814.761      194011.609     1695062.827      194087.274
#Sta/Elev= 30
     9.9  872.09    29.7  871.78    79.1  869.61      89  869.67   138.4  872.03
   168.1  872.13   207.6  868.68   217.4  867.46   227.2   865.6   236.9  862.68
   246.4  859.16   256.4  858.09   266.4  858.76   295.5  863.29     315  862.44
   451.7  866.75   461.4  867.48   481.2  870.85   491.1  872.07     561  879.89
   600.9  879.84   610.8   880.5   620.8  882.07   630.8  885.55   650.7  893.81
   670.7  901.13   700.6  913.44   710.6  919.28   720.6  928.71   730.5  934.12
#Mann= 3 , 0 , 0
       0     .06       0   246.4    .045       0   266.4     .06       0
Bank Sta=246.4,266.4
XS Rating Curve= 0 ,0
Exp/Cntr=0.3,0.1

Chan Stop Cuts=-1
Use User Specified Reach Order=0